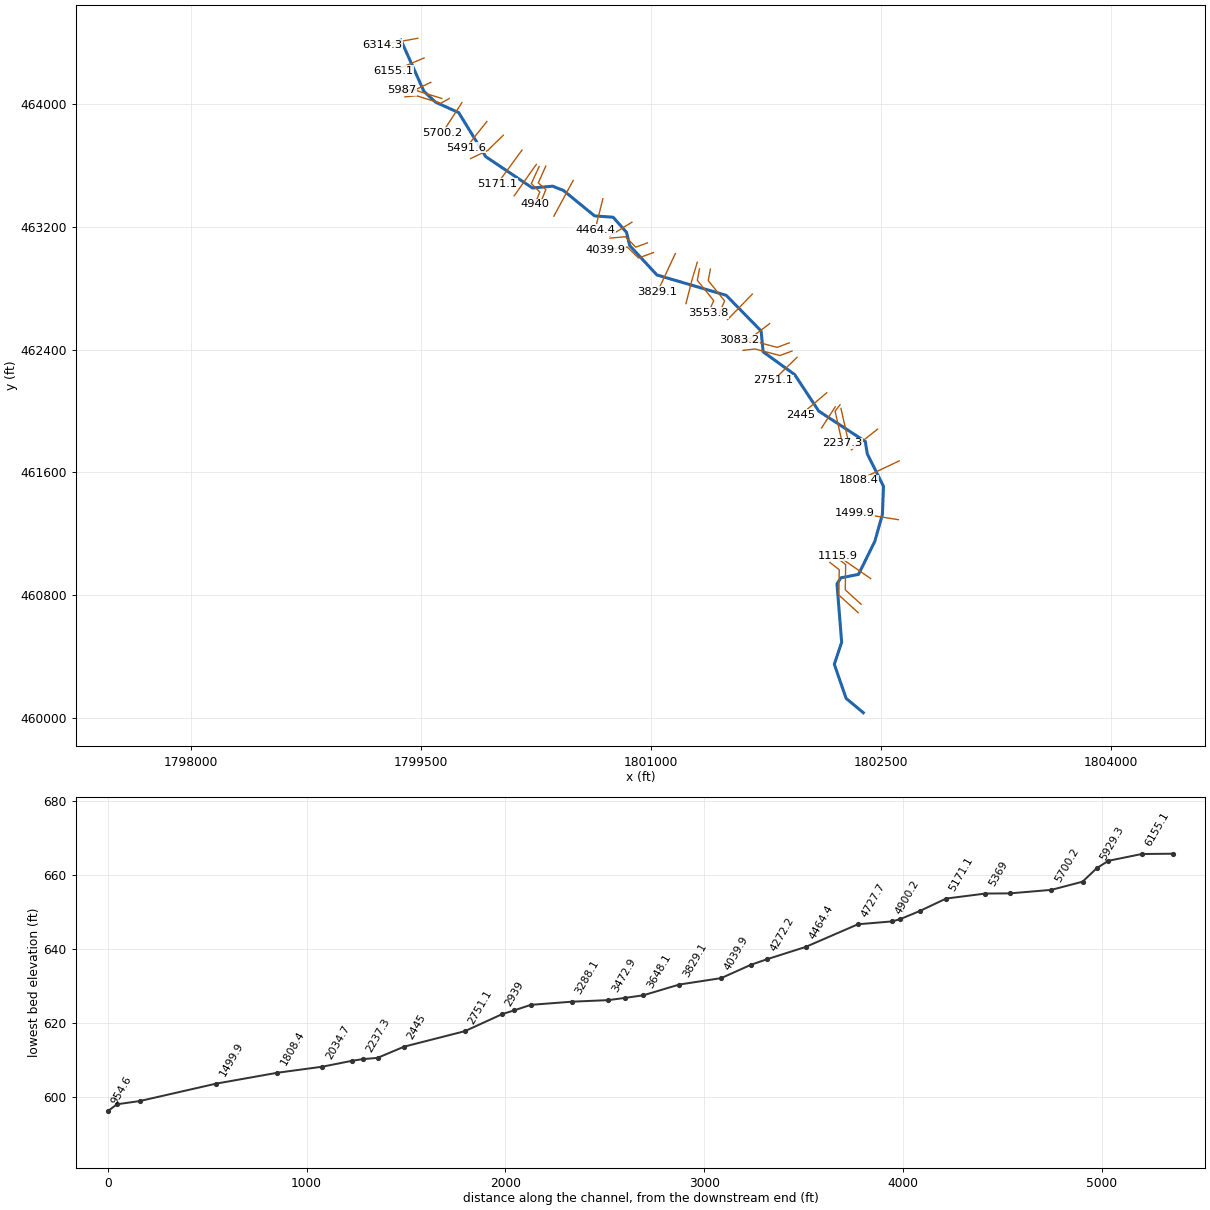
--- RFKRUSHCK.prj (project) ---

Proj Title=RFKRUSHCK
Current Plan=p01
Default Exp/Contr=0,0
English Units
Geom File=g01
Flow File=f01
Plan File=p01
BEGIN DESCRIPTION:
END DESCRIPTION:
DSS Export Rating Curves= 0
DSS Export Rating Curve Sorted= 0
DSS Export Volume Flow Curves= 0
DXF OffsetX= 0
DXF OffsetY= 0
DXF ScaleX= 0
DXF ScaleY= 0

--- RFKRUSHCK.p01 (plan) ---

Plan Title=Floodplain
Program Version=4.00
Geom File=g01
Flow File=f01
K Sum by GR=0
Std Step Tol=0.01
Critical Tol=0.01
Num of Std Step Trials=20
Max Error Tol=0.3
Flow Tol Ratio=0.001
Split Flow NTrial=30
Split Flow Tol=0.02
Split Flow Ratio=0.02
Log Output Level=0
Friction Slope Method=1
Unsteady Friction Slope Method=2
Unsteady Bridges Friction Slope Method=1
Global Log Level=0
CheckData=False
Run HTab=0
Run UNet=0
Run PostProcess=0
UNET Theta=0
UNET Theta Warmup=0
UNET ZTol=0
UNET ZSATol=0
UNET MxIter=0
UNET MaxInSteps=0
UNET DtIC=0
UNET DtMin=0
UNET MaxCRTS=0
UNET WFStab=0
UNET SFStab=0
UNET WFX=0
UNET SFX=0
UNET DSS MLevel=0
UNET DZMax Abort=0
UNET Convert EG Bridges=0
UNET Use Existing IB Tables=0
UNET Froude Limit=0
UNET Froude Power=0
Write IC File=0
Echo Input=False
Echo Output=False
Write Detailed=0

--- RFKRUSHCK.f01 (steady flow) ---

Flow Title=NFF Regression Equation
Program Version=4.10
Number of Profiles= 1
Profile Names=P100yr
River Rch & RM=RFKRUSHCK,Main            ,6314.3
939.7545
River Rch & RM=RFKRUSHCK,Main            ,5171.1
958.9064
River Rch & RM=RFKRUSHCK,Main            ,3829.1
1064.864
River Rch & RM=RFKRUSHCK,Main            ,551.9
1123.773
Boundary for River Rch & Prof#=RFKRUSHCK,Main            , 1
Up Type= 0
Dn Type= 3
Dn Slope=0.013
DSS Import GetInterval= 0
DSS Import GetPeak= 0
DSS Import FillOption= 0

--- RFKRUSHCK.g01 (geometry) ---

Geom Title=USGS 10m DEM
Program Version=4.10

River Reach=RFKRUSHCK       ,Main
Reach XY= 30
     1799372.087      464417.375     1799521.582      464083.637
     1799597.348      464013.295     1799748.647      463944.761
     1799925.039      463657.826     1800229.553       463453.79
     1800360.803      463465.508     1800431.571      463437.731
     1800634.926       463271.87      1800755.79      463263.251
     1800843.029      463165.161        1800864.      463078.513
      1801041.38      462886.949     1801493.153      462754.427
     1801720.823      462522.387     1801734.278      462386.102
     1801939.799      462237.766     1802096.864      461999.817
     1802401.303      461801.036      1802412.92      461722.594
     1802519.226      461509.192     1802512.033      461326.476
      1802462.68      461150.694     1802356.061      460935.677
     1802241.478      460913.281     1802215.957      460874.218
     1802246.375      460493.142     1802198.429      460350.075
     1802275.488      460127.474     1802387.377        460034.4

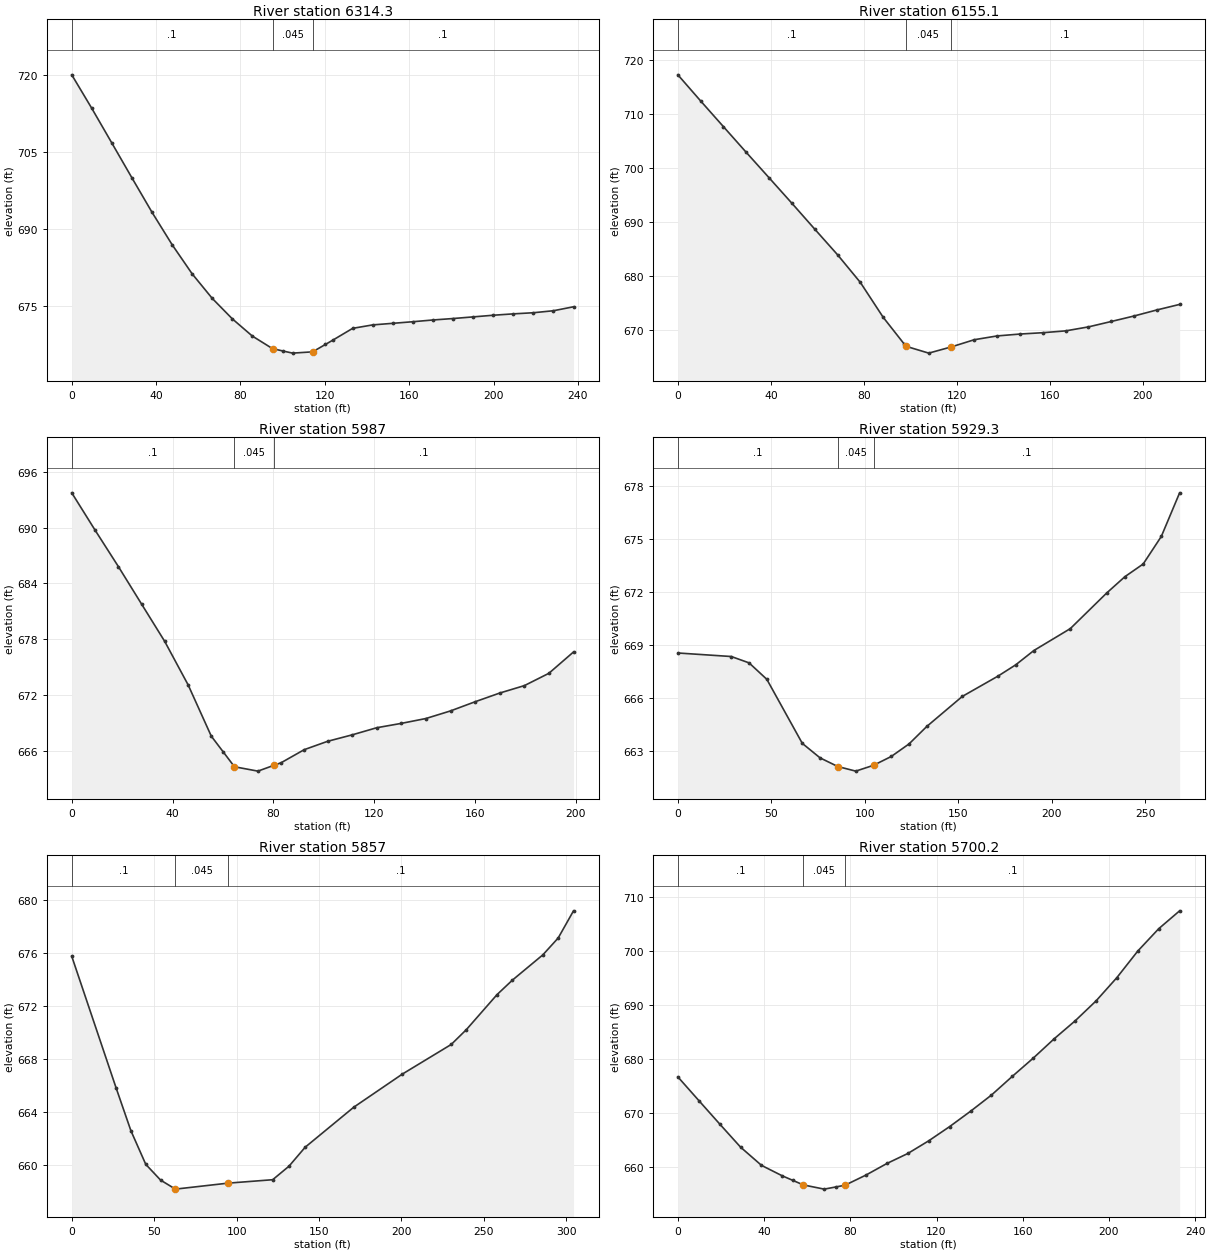
Type RM Length L Ch R = 1 ,6314.3  ,153.6,159.1,164.6
XS GIS Cut Line= 2
     1799481.725      464429.252     1799247.528      464387.418
#Sta/Elev= 28
       0  719.95     9.5  713.42      19  706.67    28.6  699.83    38.1  693.14
    47.6  686.85    57.1  681.17    66.6   676.4    76.1  672.42    85.6  669.06
    95.2   666.6   100.3  666.13   104.7  665.73   114.2  665.98   120.3  667.43
   123.7  668.24   133.2  670.56   142.7  671.23   152.3  671.54   161.8  671.85
   171.3  672.19   180.8  672.47   190.3  672.79   199.8  673.11   209.4  673.38
   218.9   673.6   228.4  673.99   237.9  674.76
#Mann= 3 , 0 , 0
       0      .1       0    95.2    .045       0   114.2      .1       0
Bank Sta=95.2,114.2
XS Rating Curve= 0 ,0
Exp/Cntr=0.3,0.1

Type RM Length L Ch R = 1 ,6155.1  ,166.9,168.1,169.3
XS GIS Cut Line= 2
     1799522.412      464300.727     1799323.338      464217.425
#Sta/Elev= 25
       0  717.29     9.8  712.44    19.6  707.67    29.4  702.91    39.2   698.2
      49  693.48    58.8  688.69    68.7  683.89    78.5  678.76    88.3   672.3
    97.3  667.36    98.1  666.92   107.9  665.65   117.3  666.77   117.7  666.82
   127.5  668.14   137.3  668.84   147.1  669.19     157  669.44   166.8  669.78
   176.6  670.52   186.4  671.52   196.2  672.54     206  673.66   215.8  674.69
#Mann= 3 , 0 , 0
       0      .1       0    98.1    .045       0   117.3      .1       0
Bank Sta=98.1,117.3
XS Rating Curve= 0 ,0
Exp/Cntr=0.3,0.1

Type RM Length L Ch R = 1 ,5987    ,99,57.6,22.2
XS GIS Cut Line= 3
     1799566.343      464142.041     1799474.676      464098.291
     1799377.454      464089.263
#Sta/Elev= 24
       0  693.75     9.2  689.76    18.5  685.82    27.7  681.79    36.9  677.77
    46.2  673.09    55.4  667.57    60.1  665.89    64.6  664.28    73.9  663.81
    80.1  664.42    83.1  664.71    92.3  666.12   101.6  667.02   111.3  667.71
   121.1  668.48   130.9  668.95   140.6  669.47   150.4  670.29   160.2  671.28
   169.9  672.21   179.7  673.01   189.4  674.33   199.2  676.63
#Mann= 3 , 0 , 0
       0      .1       0    64.6    .045       0    80.1      .1       0
Bank Sta=64.6,80.1
XS Rating Curve= 0 ,0
Exp/Cntr=0.3,0.1

Type RM Length L Ch R = 1 ,5929.3  ,70.7,72.3,65.5
XS GIS Cut Line= 3
     1799638.143      464037.195      1799465.48      464090.803
     1799378.148      464083.013
#Sta/Elev= 22
       0  668.54    28.6  668.34    38.1  667.98    47.6  667.05    66.6  663.42
    76.1   662.6    85.6  662.11    95.2  661.85   104.7  662.18   114.2  662.68
   123.7  663.39   133.2  664.38   152.2  666.08   171.3  667.23   180.8  667.87
   190.5  668.68     210  669.92   229.5  671.94   239.2  672.86     249  673.58
   258.7  675.14   268.5  677.61
#Mann= 3 , 0 , 0
       0      .1       0    85.6    .045       0   104.7      .1       0
Bank Sta=85.6,104.7
XS Rating Curve= 0 ,0
Exp/Cntr=0.3,0.1

Type RM Length L Ch R = 1 ,5857    ,102.9,156.8,212.7
XS GIS Cut Line= 4
      1799686.41      464036.942     1799631.847      464005.656
     1799472.118      464055.248     1799398.287      464047.596
#Sta/Elev= 19
       0  675.72      27  665.76    35.9  662.56    44.9  660.03    53.9  658.84
    62.9  658.16    94.7  658.61   121.9  658.87   131.8  659.89   141.6  661.32
   171.1  664.34   200.6  666.84   230.2  669.07   239.4  670.19     258  672.83
   267.3  673.92   285.8  675.83   295.1   677.1   304.4  679.15
#Mann= 3 , 0 , 0
       0      .1       0    62.9    .045       0    94.7      .1       0
Bank Sta=62.9,94.7
XS Rating Curve= 0 ,0
Exp/Cntr=0.3,0.1

Type RM Length L Ch R = 1 ,5700.2  ,211,208.7,206.2
XS GIS Cut Line= 2
     1799769.181      464009.606     1799642.594      463814.243
#Sta/Elev= 27
       0  676.73     9.7  672.36    19.4  668.01    29.1  663.72    38.8  660.35
    48.5   658.4    53.4  657.56    58.2  656.73    67.9  655.95    73.4  656.36
    77.6  656.68    87.3  658.56      97   660.7   106.7  662.55   116.4   664.9
   126.1  667.53   135.8  670.37   145.5  673.37   155.2  676.84   164.9  680.21
   174.6  683.79   184.3   687.1     194  690.79   203.7  695.12   213.4  700.04
   223.1  704.17   232.8  707.48
#Mann= 3 , 0 , 0
       0      .1       0    58.2    .045       0    77.6      .1       0
Bank Sta=58.2,77.6
XS Rating Curve= 0 ,0
Exp/Cntr=0.3,0.1

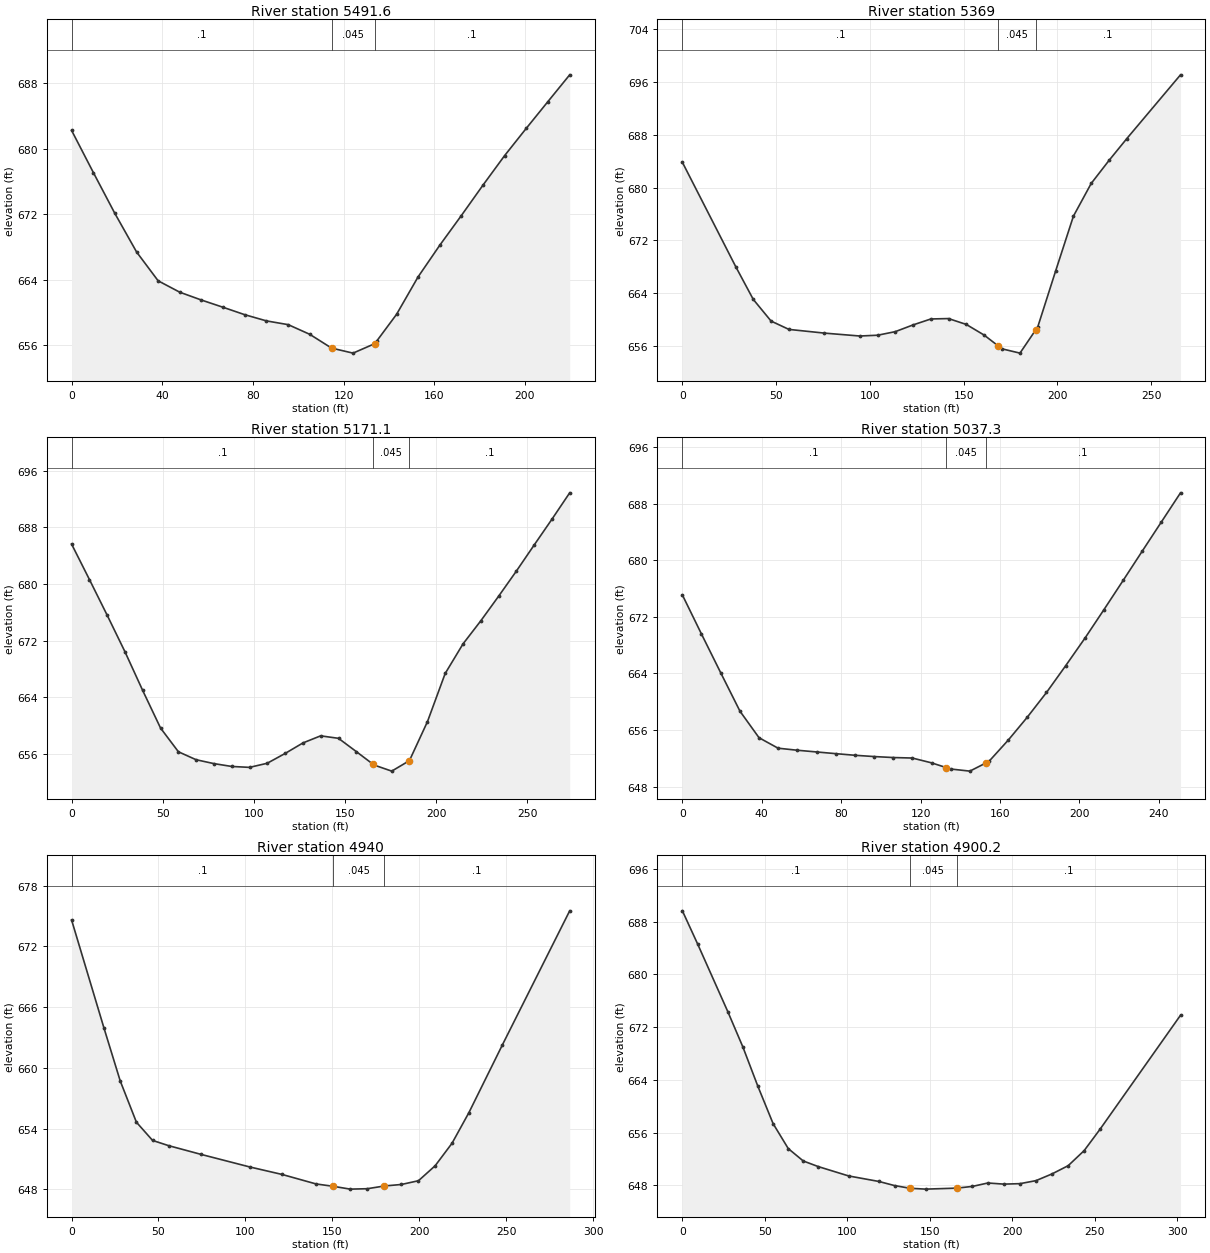
Type RM Length L Ch R = 1 ,5491.6  ,134,122.6,111.1
XS GIS Cut Line= 2
     1799932.482      463887.254     1799795.657      463715.233
#Sta/Elev= 26
       0  682.23     9.6  677.08    19.1  672.08    28.7  667.36    38.2  663.84
    47.8  662.44    57.3  661.49    66.9   660.6    76.4   659.7      86  658.94
    95.6  658.48   105.1   657.3   114.7  655.62   114.8  655.61   124.2     655
   133.8  656.16   134.8  656.53   143.4  659.74   152.9  664.32   162.5   668.2
     172  671.82   181.6  675.56   191.1  679.15   200.7   682.5   210.2  685.75
   219.8  689.02
#Mann= 3 , 0 , 0
       0      .1       0   114.8    .045       0   133.8      .1       0
Bank Sta=114.8,133.8
XS Rating Curve= 0 ,0
Exp/Cntr=0.3,0.1

Type RM Length L Ch R = 1 ,5369    ,185.2,197.9,210.2
XS GIS Cut Line= 3
      1800039.26      463797.596     1799937.871      463698.291
     1799826.065      463645.513
#Sta/Elev= 25
       0  683.83    28.4  668.06    37.8  663.08    47.3   659.8    56.8  658.54
    75.7  657.98    94.6  657.54   104.1  657.66   113.5   658.2     123  659.22
   132.5  660.12   141.9  660.18   151.4  659.29   160.9  657.68   168.4  656.04
   170.4   655.6     180  654.95   188.4  658.47   189.5  658.93     199  667.37
   208.5  675.68     218  680.64   227.5  684.12     237  687.43   265.6  697.07
#Mann= 3 , 0 , 0
       0      .1       0   168.4    .045       0   188.4      .1       0
Bank Sta=168.4,188.4
XS Rating Curve= 0 ,0
Exp/Cntr=0.3,0.1

Type RM Length L Ch R = 1 ,5171.1  ,133.1,133.8,134.1
XS GIS Cut Line= 2
     1800161.364      463700.524     1799999.688      463480.255
#Sta/Elev= 30
       0  685.65     9.8  680.64    19.5  675.62    29.3  670.44      39  664.99
    48.8  659.68    58.6  656.33    68.3  655.21    78.1  654.66    87.8  654.26
    97.6  654.13   107.3  654.71   117.1  656.09   126.9  657.58   136.6  658.58
   146.4  658.23   156.1  656.37   165.3  654.58   165.9  654.46   175.6   653.6
   185.3  655.08   195.2  660.59   204.9  667.38   214.7  671.56   224.4   674.8
   234.2  678.28     244  681.85   253.7  685.51   263.5  689.17   273.2  692.88
#Mann= 3 , 0 , 0
       0      .1       0   165.3    .045       0   185.3      .1       0
Bank Sta=165.3,185.3
XS Rating Curve= 0 ,0
Exp/Cntr=0.3,0.1

Type RM Length L Ch R = 1 ,5037.3  ,44.7,97.3,133.3
XS GIS Cut Line= 2
     1800254.997      463608.043     1800110.503      463402.901
#Sta/Elev= 29
       0  675.08     9.6  669.57    19.3  664.09      29  658.66    38.6  654.91
    48.2  653.43    57.9  653.14    67.6   652.9    77.2  652.66    86.9  652.43
    96.5  652.25   106.2  652.11   115.8  652.04   125.5  651.36   132.8   650.7
   135.1  650.49   144.8  650.19   152.8  651.33   154.4  651.56   164.1  654.56
   173.7   657.8   183.4   661.3     193  665.06   202.7  668.95   212.3  672.99
     222  677.13   231.6  681.26   241.3  685.41   250.9  689.51
#Mann= 3 , 0 , 0
       0      .1       0   132.8    .045       0   152.8      .1       0
Bank Sta=132.8,152.8
XS Rating Curve= 0 ,0
Exp/Cntr=0.3,0.1

Type RM Length L Ch R = 1 ,4940    ,54.9,39.8,41.5
XS GIS Cut Line= 4
     1800273.126      463593.102     1800222.503      463483.066
     1800277.574      463427.219     1800245.177      463346.421
#Sta/Elev= 21
       0  674.61    18.6  663.96      28  658.71    37.3  654.64    46.6  652.84
    55.9  652.32    74.5  651.46   102.5  650.22   121.1  649.48   140.7  648.54
   150.5  648.31   160.3  648.03   170.1  648.07     180  648.34   189.8  648.49
   199.6  648.86   209.2  650.34   218.9  652.56   228.6  655.58   247.9  662.28
   286.6  675.51
#Mann= 3 , 0 , 0
       0      .1       0   150.5    .045       0     180      .1       0
Bank Sta=150.5,180
XS Rating Curve= 0 ,0
Exp/Cntr=0.3,0.1

Type RM Length L Ch R = 1 ,4900.2  ,206.3,172.5,137.8
XS GIS Cut Line= 4
     1800316.408      463595.926     1800267.706      463487.149
     1800316.997      463443.222      1800272.89      463335.102
#Sta/Elev= 25
       0  689.66     9.2  684.65    27.5  674.38    36.7  668.98    45.8  663.01
      55  657.36    64.2  653.57    73.3  651.69    82.5  650.83   100.8  649.42
   119.2  648.58   128.6  647.96     138  647.55   147.5  647.42   166.3  647.57
   175.8  647.83   185.2  648.35   194.9  648.18   204.7  648.25   214.4  648.71
   224.1  649.73   233.9  650.98   243.6  653.27   253.3  656.54     302  673.81
#Mann= 3 , 0 , 0
       0      .1       0     138    .045       0   166.3      .1       0
Bank Sta=138,166.3
XS Rating Curve= 0 ,0
Exp/Cntr=0.3,0.1

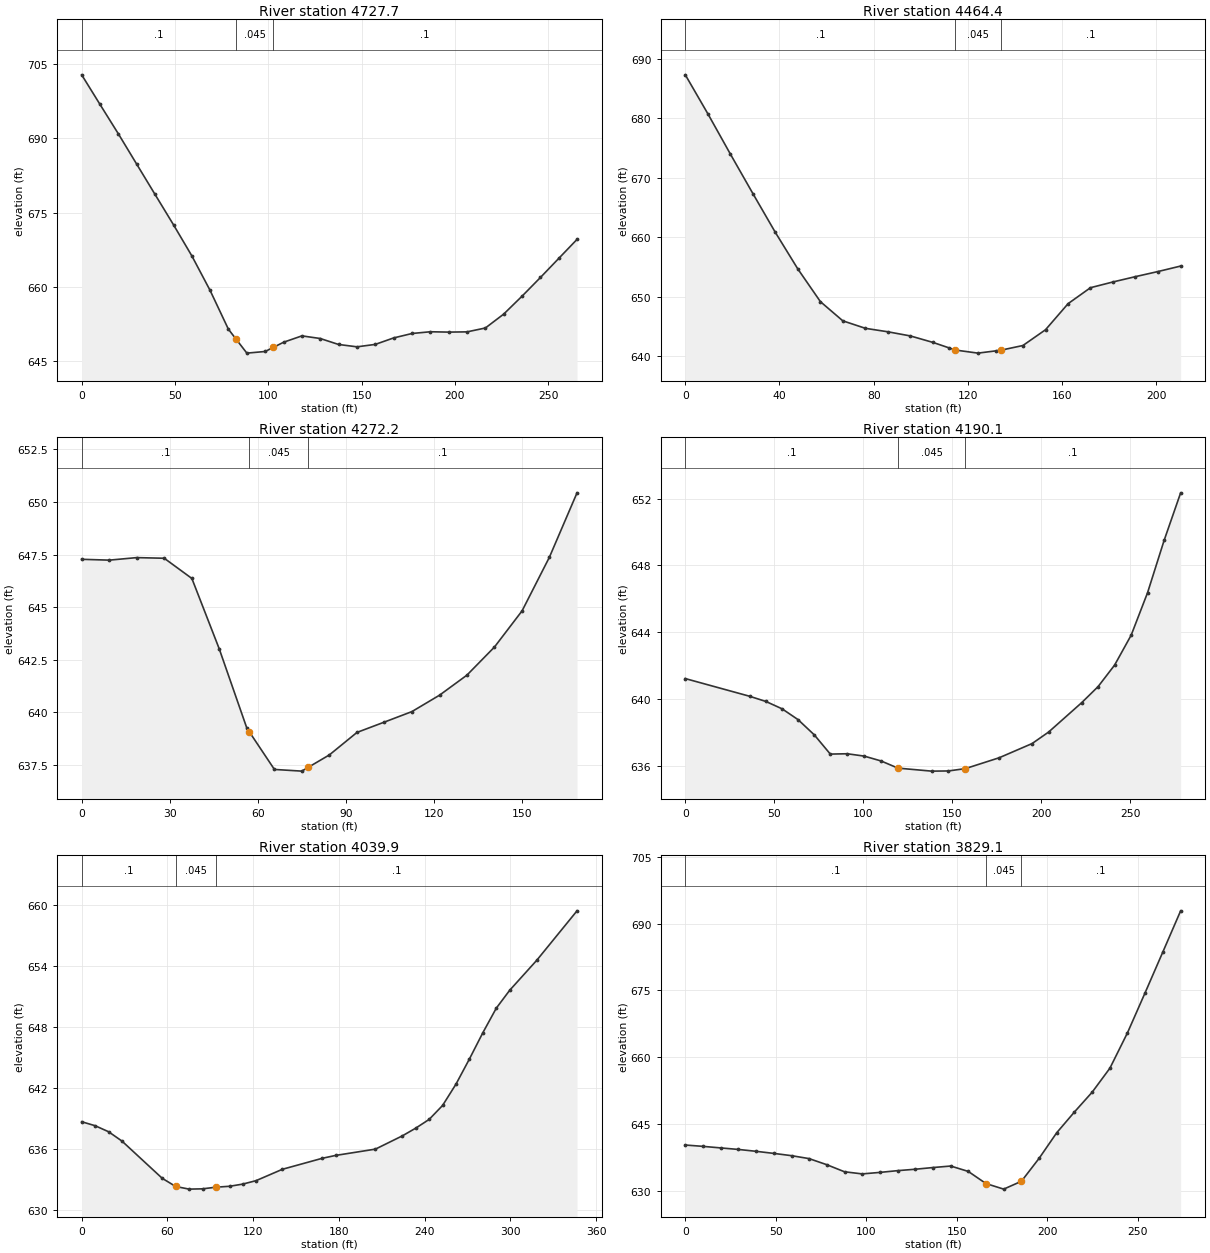
Type RM Length L Ch R = 1 ,4727.7  ,256.8,263.3,269.5
XS GIS Cut Line= 2
     1800495.771      463503.649     1800369.209      463270.316
#Sta/Elev= 30
       0  702.77     9.8  696.81    19.7  690.84    29.5  684.74    39.3  678.65
    49.2  672.52      59  666.27    68.8  659.29    78.6  651.47    82.6  649.52
    88.5  646.64    98.3  646.97   102.6  647.78   108.2  648.84     118  650.12
   127.8  649.59   137.6  648.39   147.5  647.91   157.3   648.4   167.1   649.7
     177   650.6   186.8  650.95   196.6  650.88   206.5  650.93   216.3  651.71
   226.1  654.51     236  658.15   245.8   661.9   255.6  665.74   265.4  669.58
#Mann= 3 , 0 , 0
       0      .1       0    82.6    .045       0   102.6      .1       0
Bank Sta=82.6,102.6
XS Rating Curve= 0 ,0
Exp/Cntr=0.3,0.1

Type RM Length L Ch R = 1 ,4464.4  ,211.3,192.2,172.2
XS GIS Cut Line= 2
     1800689.287      463384.129      1800637.81      463180.168
#Sta/Elev= 25
       0  687.29     9.6  680.73    19.1     674    28.7  667.33    38.2  660.83
    47.8  654.65    57.4  649.15    66.9  645.93    76.5  644.67      86  644.09
    95.6  643.39   105.2   642.3   111.9   641.4   114.7  641.02   124.3   640.5
   131.9  640.88   133.9  640.98   143.4  641.78     153  644.43   162.6  648.82
   172.1   651.5   181.7  652.47   191.2  653.36   200.8  654.22   210.4  655.14
#Mann= 3 , 0 , 0
       0      .1       0   114.7    .045       0   133.9      .1       0
Bank Sta=114.7,133.9
XS Rating Curve= 0 ,0
Exp/Cntr=0.3,0.1

Type RM Length L Ch R = 1 ,4272.2  ,159.7,82.1,55.6
XS GIS Cut Line= 2
     1800878.064      463230.624     1800734.608      463142.021
#Sta/Elev= 21
       0  647.28     9.4  647.24    18.7  647.36    28.1  647.33    37.5  646.37
    46.8  643.03    56.2  639.26    57.1  639.07    65.6  637.29    74.9  637.21
    77.1  637.39    84.3  637.98    93.7  639.05     103  639.54   112.4  640.04
   121.8  640.82   131.1  641.77   140.5  643.11   149.9  644.83   159.2  647.38
   168.6  650.44
#Mann= 3 , 0 , 0
       0      .1       0    57.1    .045       0    77.1      .1       0
Bank Sta=57.1,77.1
XS Rating Curve= 0 ,0
Exp/Cntr=0.3,0.1

Type RM Length L Ch R = 1 ,4190.1  ,77.9,150.2,70.9
XS GIS Cut Line= 4
     1800979.725      463096.031     1800903.137      463068.071
     1800837.086      463136.149     1800735.498       463127.07
#Sta/Elev= 24
       0  641.23    36.2  640.17    45.3  639.86    54.4  639.42    63.4  638.77
    72.5  637.86    81.5  636.71      91  636.73   100.5  636.59     110   636.3
   119.5  635.87   138.4  635.69   147.8   635.7   157.4  635.84   176.4  636.49
   194.9  637.34   204.2  638.03   222.8  639.79     232  640.75   241.3  642.04
   250.6  643.83   259.8  646.37   269.1   649.5   278.4  652.35
#Mann= 3 , 0 , 0
       0      .1       0   119.5    .045       0   157.4      .1       0
Bank Sta=119.5,157.4
XS Rating Curve= 0 ,0
Exp/Cntr=0.3,0.1

Type RM Length L Ch R = 1 ,4039.9  ,190.8,210.7,330.5
XS GIS Cut Line= 4
     1801018.464       463032.84     1800921.349       462997.46
     1800848.186       463068.86     1800708.177      463051.374
#Sta/Elev= 27
       0  638.69     9.4   638.3    18.8  637.71    28.2  636.79    56.4  633.13
    65.8  632.33    75.2  632.07    84.6   632.1      94  632.26   103.5  632.35
   112.6  632.56     122   632.9   140.5  634.02   168.4   635.1   177.7  635.38
   205.6     636   224.4   637.3   233.8  638.06   243.2  638.92   252.6  640.29
     262  642.39   271.4  644.86   280.8  647.44   290.2  649.85   299.6  651.61
   318.5  654.55   346.7  659.41
#Mann= 3 , 0 , 0
       0      .1       0    65.8    .045       0      94      .1       0
Bank Sta=65.8,94
XS Rating Curve= 0 ,0
Exp/Cntr=0.3,0.1

Type RM Length L Ch R = 1 ,3829.1  ,176.3,181,185.8
XS GIS Cut Line= 2
     1801161.609      463026.291     1801045.478      462778.359
#Sta/Elev= 30
       0  640.24     9.8  639.94    19.6  639.59    29.3  639.25    39.1  638.83
    48.9  638.36    58.7  637.85    68.4  637.19    78.2  635.82      88  634.23
    97.8  633.75   107.6  634.09   117.3  634.48   127.1   634.8   136.9  635.18
   146.7  635.52   156.4  634.31   165.8  631.69   166.2  631.58     176  630.33
   185.8   632.1   195.6  637.27   205.3     643   215.1  647.67   224.9  652.12
   234.7  657.51   244.4  665.45   254.2   674.5     264  683.66   273.8  692.87
#Mann= 3 , 0 , 0
       0      .1       0   166.2    .045       0   185.8      .1       0
Bank Sta=166.2,185.8
XS Rating Curve= 0 ,0
Exp/Cntr=0.3,0.1

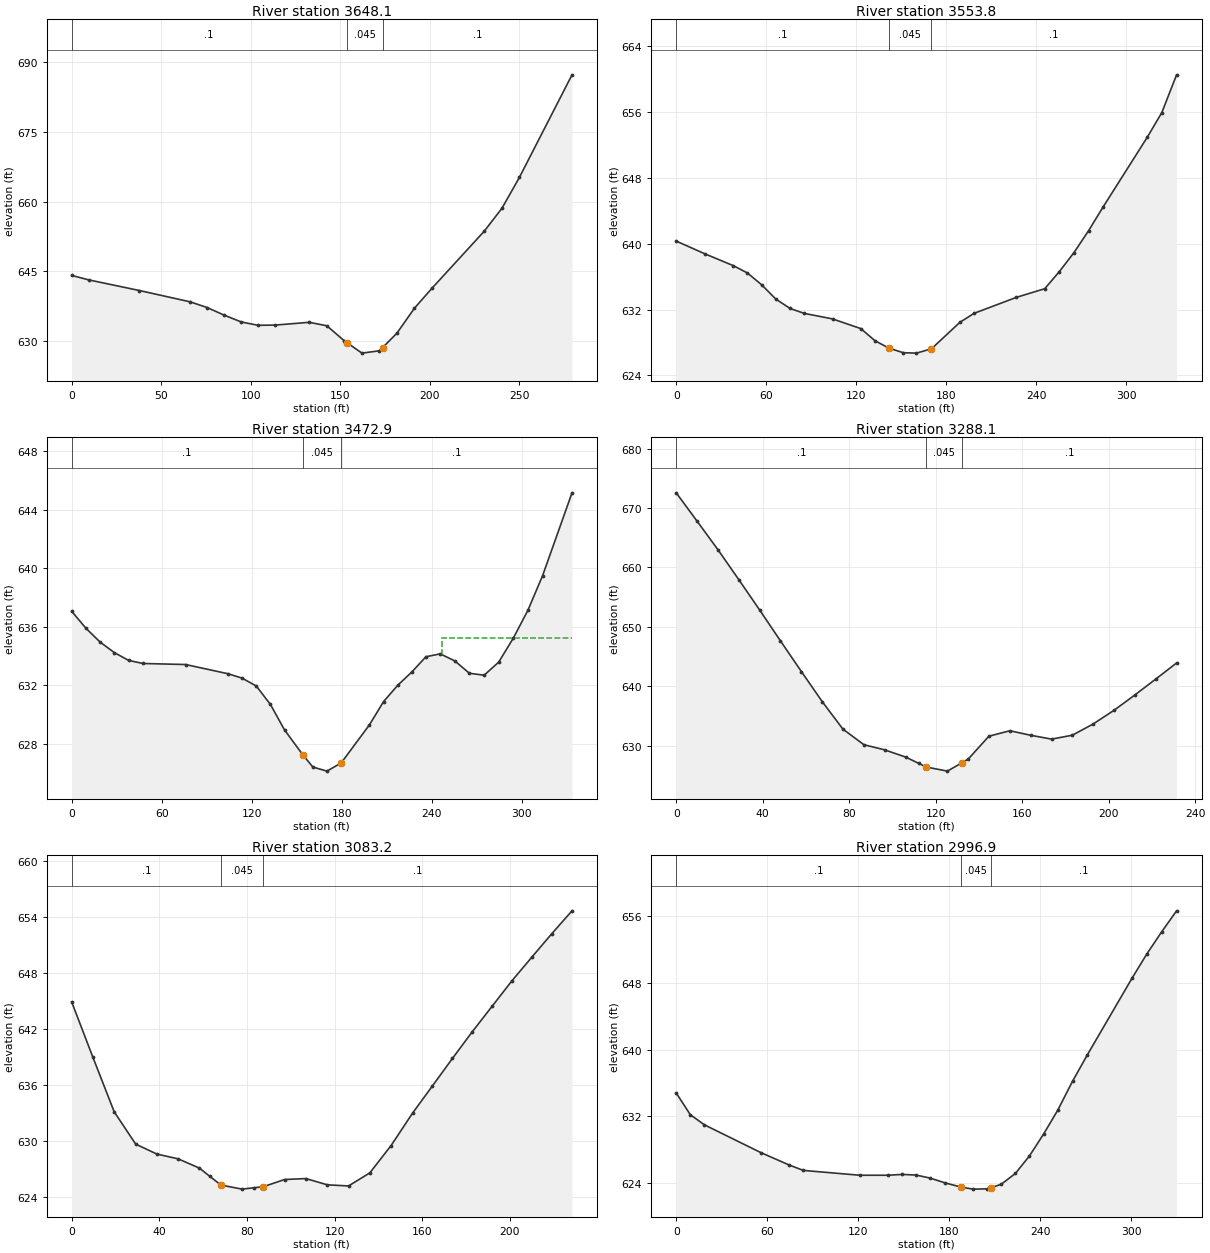
Type RM Length L Ch R = 1 ,3648.1  ,64.3,94.3,122.5
XS GIS Cut Line= 3
     1801304.552      462969.561     1801269.256      462851.777
     1801230.941      462700.117
#Sta/Elev= 23
       0  644.14     9.5  643.18    37.8  640.89    66.2  638.45    75.7  637.22
    85.1   635.6    94.6  634.14     104  633.41   113.5  633.45   132.7  634.05
   142.5   633.3   152.3  630.05   153.6   629.7   162.1  627.42   171.8  627.92
   173.6  628.61   181.6   631.7   191.4  637.08   201.2  641.38   230.5   653.7
   240.3   658.6     250  665.21   279.4  687.29
#Mann= 3 , 0 , 0
       0      .1       0   153.6    .045       0   173.6      .1       0
Bank Sta=153.6,173.6
XS Rating Curve= 0 ,0
Exp/Cntr=0.3,0.1

Type RM Length L Ch R = 1 ,3553.8  ,78.7,80.9,91.7
XS GIS Cut Line= 4
     1801318.836      462926.569     1801304.947      462851.916
     1801411.718      462719.972     1801376.996      462639.242
#Sta/Elev= 26
       0  640.32      19  638.78      38  637.34    47.5  636.44      57     635
    66.4  633.27    75.9  632.13    85.4  631.53   104.2  630.86   123.1  629.68
   132.5  628.21   141.9   627.3   151.4  626.75   160.2   626.7   170.2  627.23
   189.1  630.44   198.5  631.53   226.8  633.48   245.7  634.53   255.4   636.6
   265.2  638.92     275   641.6   284.7  644.49     314  652.92   323.8  655.95
   333.6  660.53
#Mann= 3 , 0 , 0
       0      .1       0   141.9    .045       0   170.2      .1       0
Bank Sta=141.9,170.2
XS Rating Curve= 0 ,0
Exp/Cntr=0.3,0.1

Type RM Length L Ch R = 1 ,3472.9  ,230.1,184.8,132.6
XS GIS Cut Line= 4
     1801390.017      462924.833     1801376.128       462850.18
     1801482.899      462718.236     1801448.176      462637.506
#Sta/Elev= 30
       0  637.05     9.5  635.89      19  634.94    28.5  634.22      38  633.69
    47.5  633.48    75.9  633.41   104.2  632.78   113.6  632.48   123.1  631.94
   132.5  630.68   141.9  628.94     154  627.25   160.8   626.4   170.2  626.12
   179.7  626.68   198.5  629.28     208  630.88   217.4  631.99   226.8   632.9
   236.2  633.94   245.7  634.14   255.4  633.66   265.2  632.81     275  632.68
   284.7  633.57   294.5  635.22   304.2  637.12     314  639.49   333.6  645.15
#Mann= 3 , 0 , 0
       0      .1       0     154    .045       0   179.7      .1       0
#XS Ineff= 2 , 0
                          247.16           635.2
Permanent Ineff=
       F       F
Bank Sta=154,179.7
XS Rating Curve= 0 ,0
Exp/Cntr=0.3,0.1

Type RM Length L Ch R = 1 ,3288.1  ,208.5,204.9,201
XS GIS Cut Line= 2
     1801663.489      462761.764     1801502.031      462595.965
#Sta/Elev= 27
       0  672.56     9.6  667.81    19.3  662.98    28.9  657.96    38.6  652.82
    48.2  647.63    57.9  642.45    67.5  637.41    77.1  632.76    86.8  630.14
    96.4  629.27   106.1  628.06   112.2  626.99   115.7  626.38   125.4  625.69
   132.2  627.11     135   627.7   144.6  631.57   154.3  632.49   163.9  631.73
   173.6  631.08   183.2  631.74   192.8  633.62   202.5  635.94   212.1  638.51
   221.8   641.2   231.4   643.9
#Mann= 3 , 0 , 0
       0      .1       0   115.7    .045       0   132.2      .1       0
Bank Sta=115.7,132.2
XS Rating Curve= 0 ,0
Exp/Cntr=0.3,0.1

Type RM Length L Ch R = 1 ,3083.2  ,108.9,86.3,63.2
XS GIS Cut Line= 3
     1801776.311      462569.665      1801652.42      462475.599
     1801580.532      462464.128
#Sta/Elev= 27
       0  644.87     9.7  638.94    19.4  633.12    29.2  629.66    38.9  628.59
    48.6  628.08    58.3  627.09      63  626.22    68.1  625.28    77.8  624.84
      83  624.98    87.5   625.1    97.2  625.87   106.9  625.97   116.7   625.3
   126.4  625.18   136.1  626.58   145.8   629.5   155.6  632.97   164.7  635.89
   173.8  638.82   182.8  641.66     192  644.43     201  647.14   210.2   649.7
   219.2  652.18   228.4  654.62
#Mann= 3 , 0 , 0
       0      .1       0    68.1    .045       0    87.5      .1       0
Bank Sta=68.1,87.5
XS Rating Curve= 0 ,0
Exp/Cntr=0.3,0.1

Type RM Length L Ch R = 1 ,2996.9  ,76.4,57.9,50.8
XS GIS Cut Line= 4
     1801904.273      462444.386     1801825.757       462415.23
     1801663.518        462457.9      1801585.65      462448.882
#Sta/Elev= 27
       0  634.81     9.3  632.21    18.6     631    55.8  627.68    74.4   626.2
    83.8  625.55     121  624.97   139.7  624.97     149  625.07   158.3  624.99
   167.6  624.62     177  624.07   187.7  623.56   195.6  623.31   204.9  623.34
   207.7   623.5   214.2  623.88   223.6  625.18   232.9  627.28   242.2  629.89
   251.5  632.73   261.3  636.21   271.1  639.38   300.5  648.53   310.3  651.44
   320.1  654.09   329.9   656.6
#Mann= 3 , 0 , 0
       0      .1       0   187.7    .045       0   207.7      .1       0
Bank Sta=187.7,207.7
XS Rating Curve= 0 ,0
Exp/Cntr=0.3,0.1

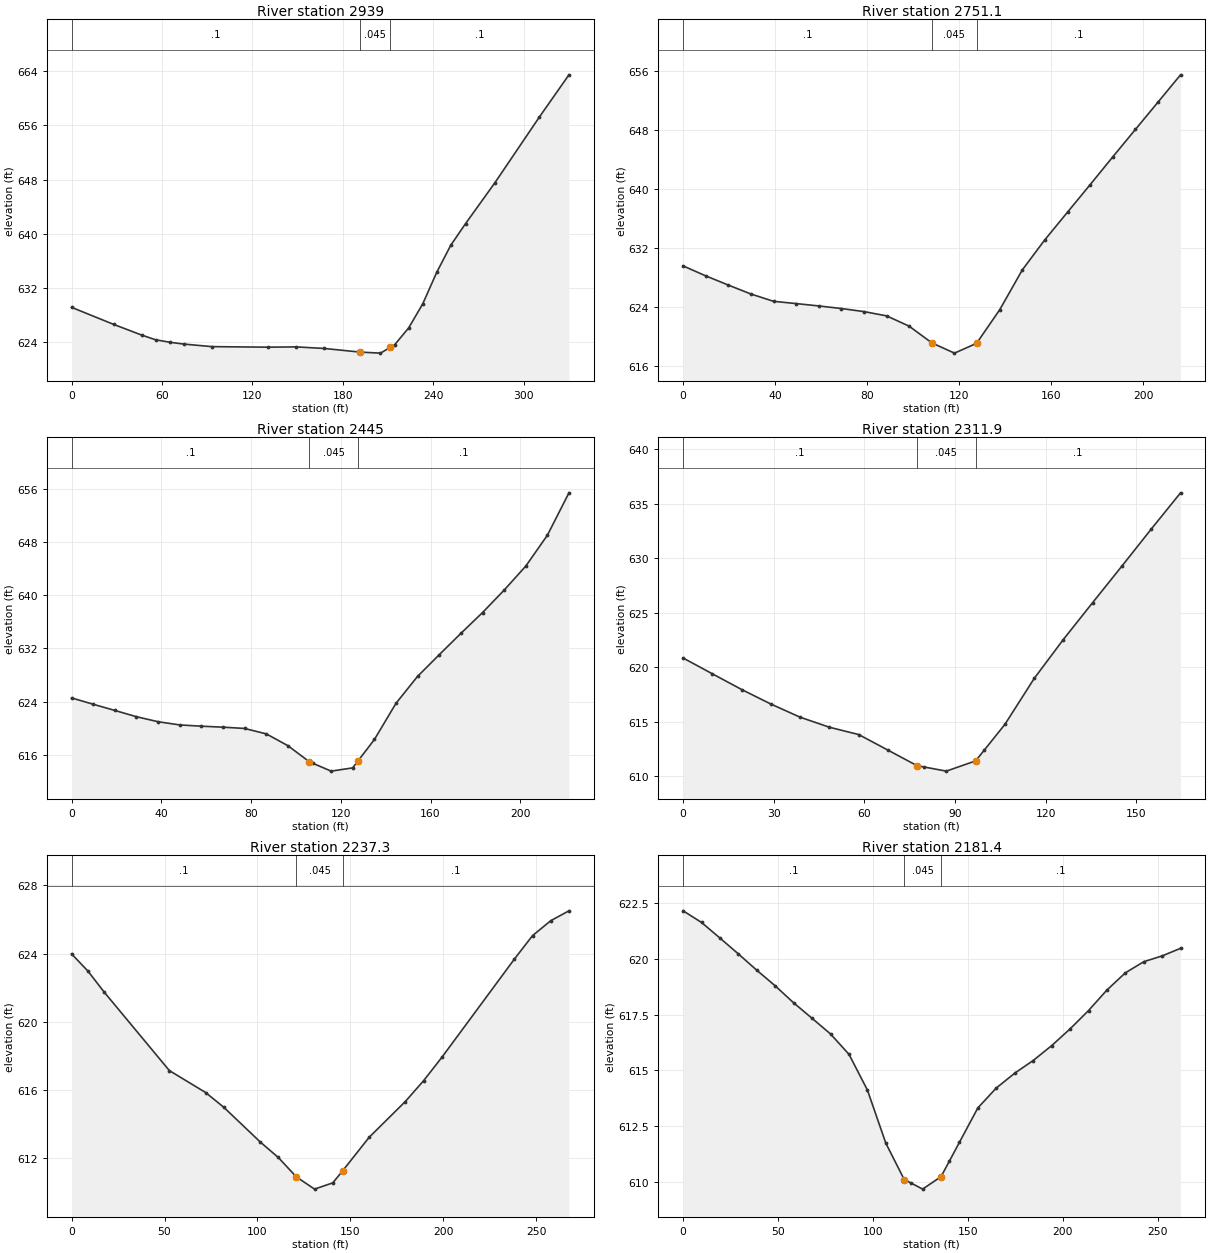
Type RM Length L Ch R = 1 ,2939    ,142.8,187.9,221.1
XS GIS Cut Line= 4
     1801922.246      462391.132      1801843.73      462361.976
     1801681.491      462404.645     1801603.623      462395.628
#Sta/Elev= 22
       0  629.11    27.9  626.59    46.5  625.01    55.8  624.31    65.1  623.95
    74.4  623.68    93.1   623.3   130.4  623.22     149  623.26   167.6  623.03
   191.4  622.49   204.9  622.34   211.4  623.19   214.2  623.55   223.6  626.07
   232.9  629.61   242.2  634.28   251.5  638.28   261.3  641.48   280.9  647.56
   310.3  657.25   329.9  663.48
#Mann= 3 , 0 , 0
       0      .1       0   191.4    .045       0   211.4      .1       0
Bank Sta=191.4,211.4
XS Rating Curve= 0 ,0
Exp/Cntr=0.3,0.1

Type RM Length L Ch R = 1 ,2751.1  ,307.7,306.1,303.9
XS GIS Cut Line= 2
     1801955.266      462350.178     1801800.019       462199.52
#Sta/Elev= 24
       0  629.57     9.8  628.22    19.7  626.96    29.5  625.75    39.3  624.76
    49.2  624.45      59  624.13    68.8  623.78    78.7  623.36    88.5  622.78
    98.3  621.38   107.6  619.24   108.2   619.1     118  617.72   127.6  619.05
   137.7  623.63   147.5  629.03   157.3  633.12   167.2  636.89     177  640.61
   186.8  644.37   196.7  648.12   206.5  651.82   216.3  655.53
#Mann= 3 , 0 , 0
       0      .1       0   108.2    .045       0   127.6      .1       0
Bank Sta=108.2,127.6
XS Rating Curve= 0 ,0
Exp/Cntr=0.3,0.1

Type RM Length L Ch R = 1 ,2445    ,125.9,133.1,140.5
XS GIS Cut Line= 2
     1802148.865       462119.07     1801979.594      461975.841
#Sta/Elev= 26
       0  624.55     9.6   623.6    19.3  622.66    28.9  621.72    38.6  620.96
    48.2  620.48    57.8  620.29    67.5  620.14    77.1  619.95    86.8  619.13
    96.4  617.36     106  614.93   107.5  614.71   115.7  613.52   125.3  614.01
   127.5  614.98     135  618.29   144.6  623.73   154.2  627.78   163.9  631.06
   173.5  634.26   183.2  637.41   192.8  640.78   202.5  644.42   212.1  649.06
   221.7  655.44
#Mann= 3 , 0 , 0
       0      .1       0     106    .045       0   127.5      .1       0
Bank Sta=106,127.5
XS Rating Curve= 0 ,0
Exp/Cntr=0.3,0.1

Type RM Length L Ch R = 1 ,2311.9  ,51.5,74.6,97.8
XS GIS Cut Line= 2
     1802204.903      462028.098     1802115.228      461890.121
#Sta/Elev= 20
       0  620.85     9.7   619.4    19.4  617.96      29  616.64    38.7  615.43
    48.4  614.51    58.1  613.84    67.8  612.41    77.4  610.99    79.7  610.87
    87.1  610.49    96.8  611.43    99.7  612.43   106.5  614.78   116.2  618.99
   125.8  622.54   135.5  625.92   145.2  629.27   154.9  632.66   164.6  635.98
#Mann= 3 , 0 , 0
       0      .1       0    77.4    .045       0    96.8      .1       0
Bank Sta=77.4,96.8
XS Rating Curve= 0 ,0
Exp/Cntr=0.3,0.1

Type RM Length L Ch R = 1 ,2237.3  ,54,55.9,56.8
XS GIS Cut Line= 3
     1802235.671      462040.945     1802203.585       461999.33
     1802250.701      461789.645
#Sta/Elev= 20
       0  623.98     8.8  622.97    17.5  621.74    52.6  617.12    72.1  615.83
    81.8  614.97   101.4  612.93   111.2  612.01   120.9  610.87   130.7  610.15
   140.5  610.52   145.9  611.24     160  613.19   179.5   615.3   189.3  616.52
   199.1  617.89   238.2  623.68   247.9  625.05   257.7  625.93   267.5  626.51
#Mann= 3 , 0 , 0
       0      .1       0   120.9    .045       0   145.9      .1       0
Bank Sta=120.9,145.9
XS Rating Curve= 0 ,0
Exp/Cntr=0.3,0.1

Type RM Length L Ch R = 1 ,2181.4  ,179.8,146.7,114.4
XS GIS Cut Line= 2
     1802241.893      462017.358     1802299.357      461761.615
#Sta/Elev= 30
       0  622.15     9.7  621.63    19.4  620.93    29.1  620.22    38.8  619.49
    48.5  618.79    58.2  618.03      68  617.33    77.7  616.63    87.4  615.72
    97.1  614.12   106.8  611.74   116.5  610.11   120.2  609.95   126.2  609.68
   135.9  610.24   140.2  610.92   145.6  611.78   155.3  613.32     165  614.21
   174.8  614.88   184.4  615.44   194.2  616.11   203.9  616.86   213.6  617.68
   223.3   618.6     233  619.37   242.7  619.87   252.4  620.13   262.1  620.47
#Mann= 3 , 0 , 0
       0      .1       0   116.5    .045       0   135.9      .1       0
Bank Sta=116.5,135.9
XS Rating Curve= 0 ,0
Exp/Cntr=0.3,0.1

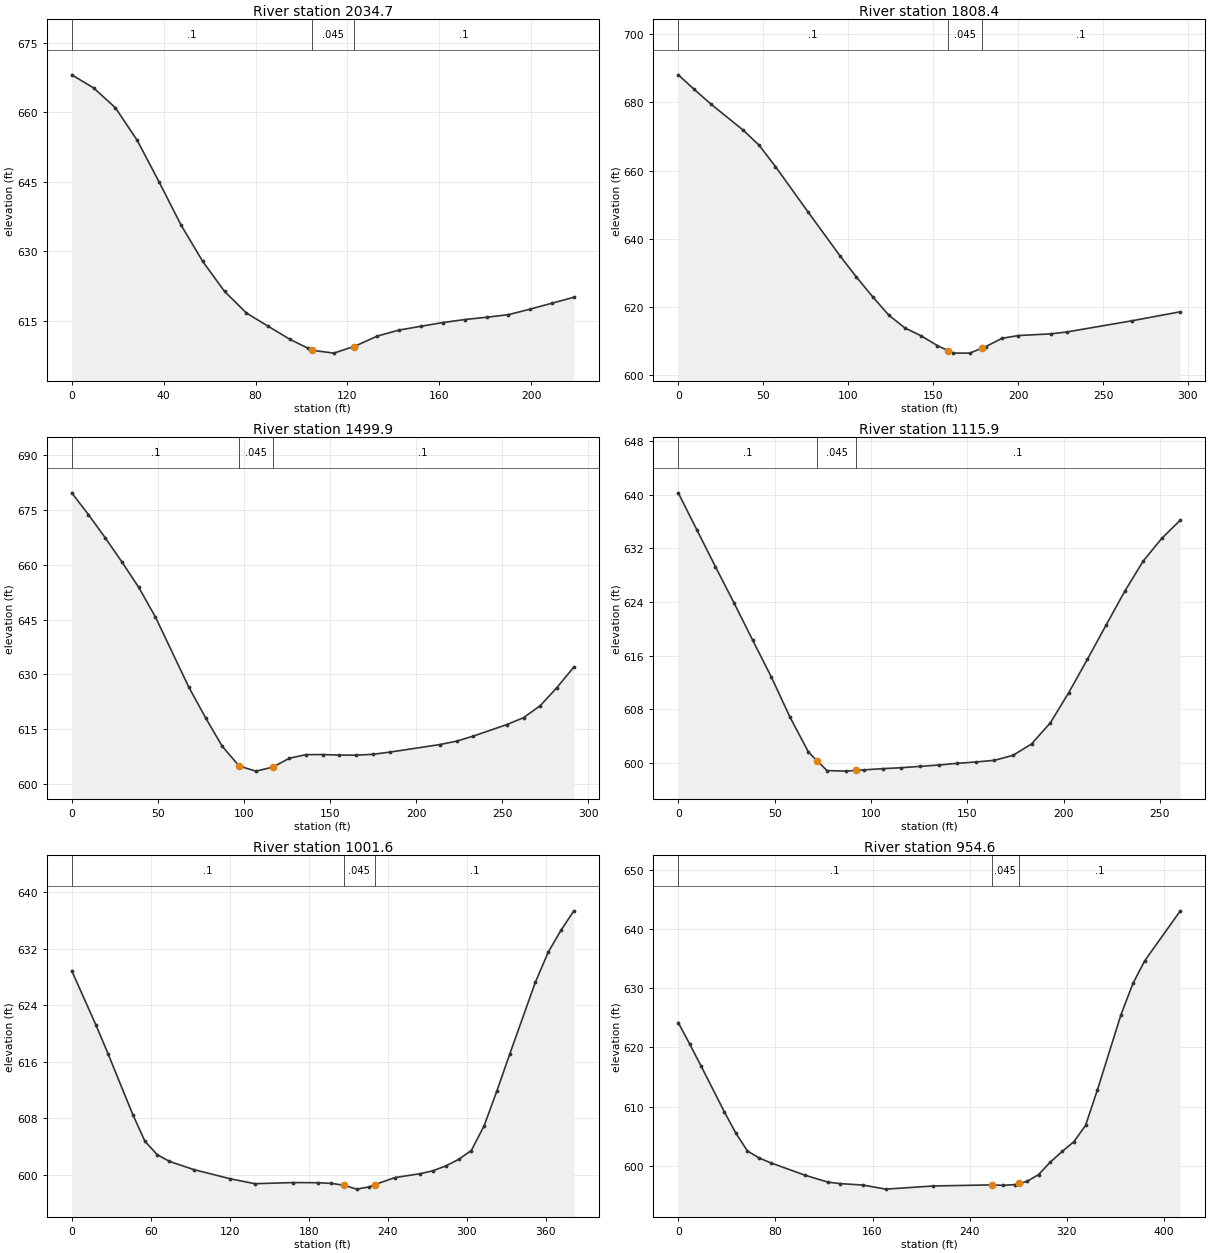
Type RM Length L Ch R = 1 ,2034.7  ,231.6,226.2,219.9
XS GIS Cut Line= 2
     1802480.896      461882.525     1802309.455      461746.892
#Sta/Elev= 26
       0  668.05     9.5  665.23      19  660.96    28.5  653.93      38     645
    47.5  635.77      57  627.88    66.5  621.42      76  616.77    85.5   613.9
      95  611.08   102.7   609.2   104.6  608.73   114.1  608.11   122.7  609.52
   123.6  609.67   133.1   611.8   142.6  613.09   152.1   613.9   161.6   614.7
   171.1  615.34   180.6  615.84   190.1  616.39   199.6  617.59   209.1  618.87
   218.6  620.14
#Mann= 3 , 0 , 0
       0      .1       0   104.6    .045       0   122.7      .1       0
Bank Sta=104.6,122.7
XS Rating Curve= 0 ,0
Exp/Cntr=0.3,0.1

Type RM Length L Ch R = 1 ,1808.4  ,323.4,308.5,293.4
XS GIS Cut Line= 2
     1802621.722      461675.147     1802354.361      461549.278
#Sta/Elev= 25
       0   688.1     9.5   683.8    19.1  679.58    38.1  671.93    47.7   667.4
    57.2  661.21    76.3  647.95    95.3  634.95   104.9  628.77   114.4  623.03
   123.9  617.62   133.5  613.83     143  611.54   152.5  608.68   158.7  607.24
     162  606.48   171.6  606.47   178.7  607.92   181.1  608.41   190.6  610.82
   200.2  611.63   219.2  612.12   228.8  612.68   266.9  615.95   295.5   618.6
#Mann= 3 , 0 , 0
       0      .1       0   158.7    .045       0   178.7      .1       0
Bank Sta=158.7,178.7
XS Rating Curve= 0 ,0
Exp/Cntr=0.3,0.1

Type RM Length L Ch R = 1 ,1499.9  ,394.9,384,372.4
XS GIS Cut Line= 2
     1802616.258      461292.272     1802328.394      461337.915
#Sta/Elev= 27
       0  679.68     9.7  673.71    19.4  667.39    29.2  660.71    38.9  653.79
    48.6  645.68      68  626.46    77.7  618.12    87.4  610.29    97.2  604.91
   106.9  603.52   116.6   604.6   126.3  607.04     136  608.03   145.7  608.06
   155.4  607.91   165.2  607.89   174.9  608.13   184.6  608.72   213.7  610.79
   223.4  611.72   233.2  613.12   252.6  616.26   262.3  618.15     272  621.44
   281.7   626.4   291.5  632.01
#Mann= 3 , 0 , 0
       0      .1       0    97.2    .045       0   116.6      .1       0
Bank Sta=97.2,116.6
XS Rating Curve= 0 ,0
Exp/Cntr=0.3,0.1

Type RM Length L Ch R = 1 ,1115.9  ,139.2,114.4,89.5
XS GIS Cut Line= 2
     1802435.465      460908.428     1802221.028      461056.579
#Sta/Elev= 30
       0  640.28     9.6  634.81    19.3  629.28      29  623.85    38.6  618.35
    48.3  612.85    57.9  606.92    67.6  601.64    72.2  600.33    77.2   598.9
    86.9  598.81    92.2  598.91    96.5     599   106.2  599.18   115.8  599.32
   125.5  599.52   135.2  599.72   144.8  599.97   154.4  600.17   164.1  600.42
   173.8  601.17   183.4  602.87   193.1  605.99   202.7  610.51   212.4  615.49
     222  620.53   231.7  625.58   241.3   630.1     251   633.5   260.6  636.21
#Mann= 3 , 0 , 0
       0      .1       0    72.2    .045       0    92.2      .1       0
Bank Sta=72.2,92.2
XS Rating Curve= 0 ,0
Exp/Cntr=0.3,0.1

Type RM Length L Ch R = 1 ,1001.6  ,118.8,47,41.5
XS GIS Cut Line= 4
     1802372.799      460741.512     1802269.884      460835.052
     1802272.385      460999.467     1802211.189      461047.704
#Sta/Elev= 30
       0  628.88    18.5  621.14    27.8  617.02    46.4  608.49    55.6  604.72
    64.9  602.83    74.2  601.87    92.7  600.71   120.5   599.4   139.1  598.71
   168.1  598.87   187.4  598.85   197.1  598.75   206.8   598.5   216.4  597.94
   226.1  598.27   230.2  598.58   245.5  599.58   264.8  600.13   274.5  600.55
   284.2  601.23   293.8  602.15   303.5  603.41   313.2   606.9     323  611.89
   332.7  617.08   352.2  627.28     362  631.54   371.7  634.65   381.4  637.38
#Mann= 3 , 0 , 0
       0      .1       0   206.8    .045       0   230.2      .1       0
Bank Sta=206.8,230.2
XS Rating Curve= 0 ,0
Exp/Cntr=0.3,0.1

Type RM Length L Ch R = 1 ,954.6   ,130.5,244.2,291.2
XS GIS Cut Line= 4
     1802354.385      460685.657     1802228.178      460801.023
     1802230.679      460965.438     1802169.483      461013.675
#Sta/Elev= 29
       0  624.22     9.5  620.56      19  616.79      38  609.11    47.5  605.48
      57   602.5    66.5  601.32      76   600.5   104.5  598.39   123.5  597.21
     133  596.98     152  596.73     171  596.04   209.7  596.57     258  596.76
   267.7  596.68   277.4  596.81   280.8     597   287.1  597.34   296.7   598.5
   306.4  600.62   316.1  602.41   325.8  604.07   335.4  606.83   345.2  612.86
   364.6  625.58   374.4  630.84   384.1  634.67   413.4  643.12
#Mann= 3 , 0 , 0
       0      .1       0     258    .045       0   280.8      .1       0
Bank Sta=258,280.8
XS Rating Curve= 0 ,0
Exp/Cntr=0.3,0.1