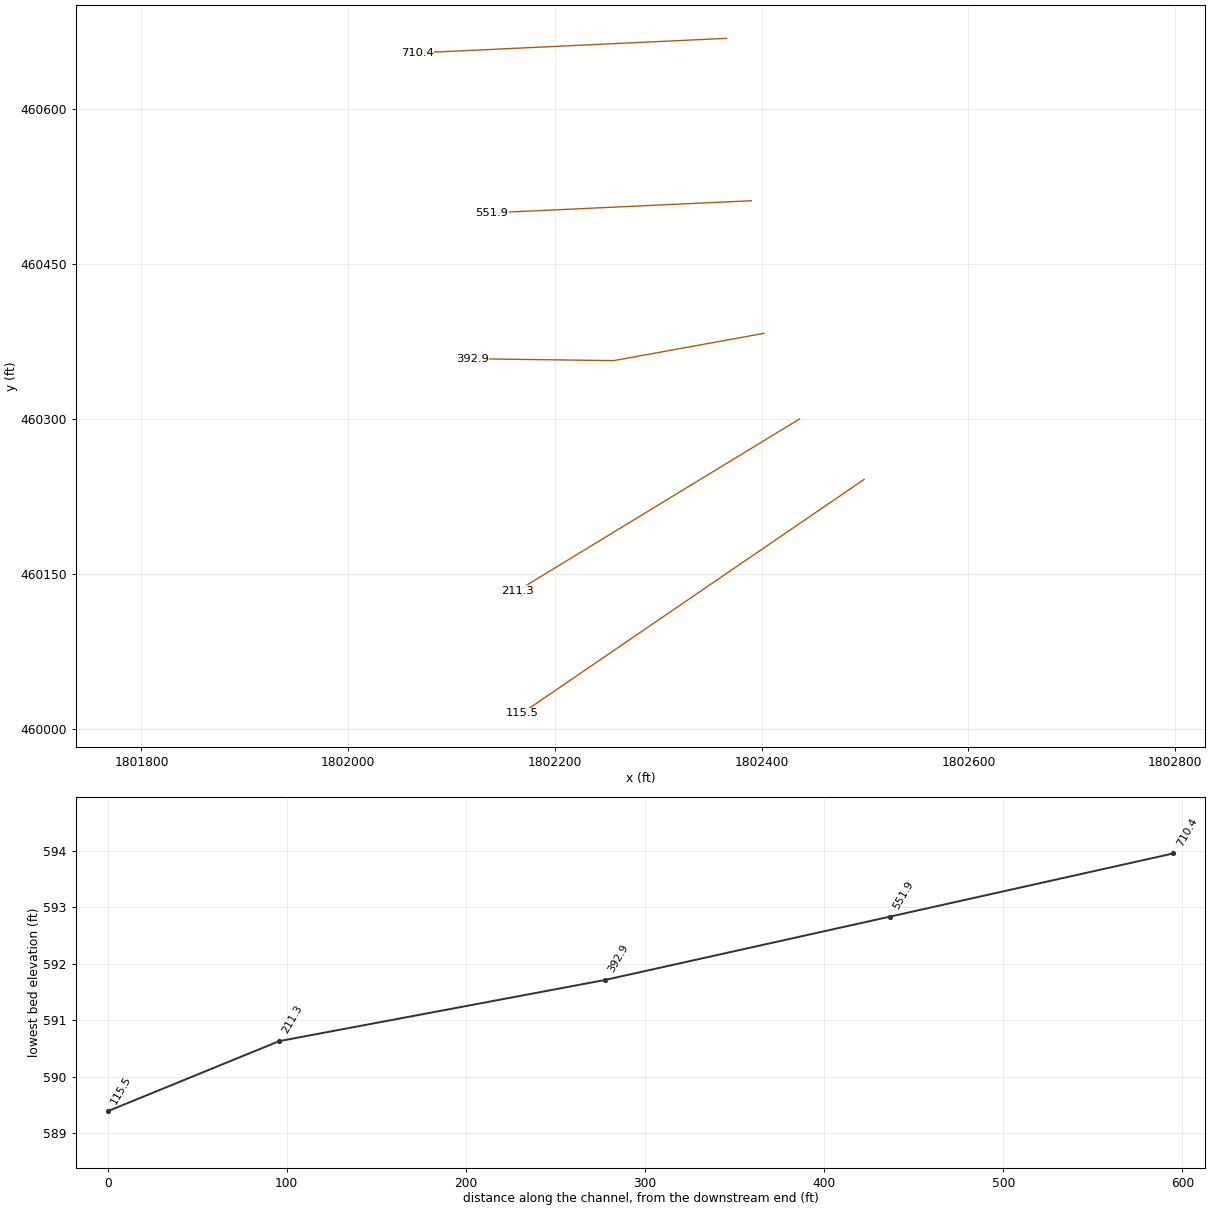
HEC-RAS study RFKRUSHCK.prj: RFKRUSHCK

--- RFKRUSHCK.g01 (geometry) --- (continued)

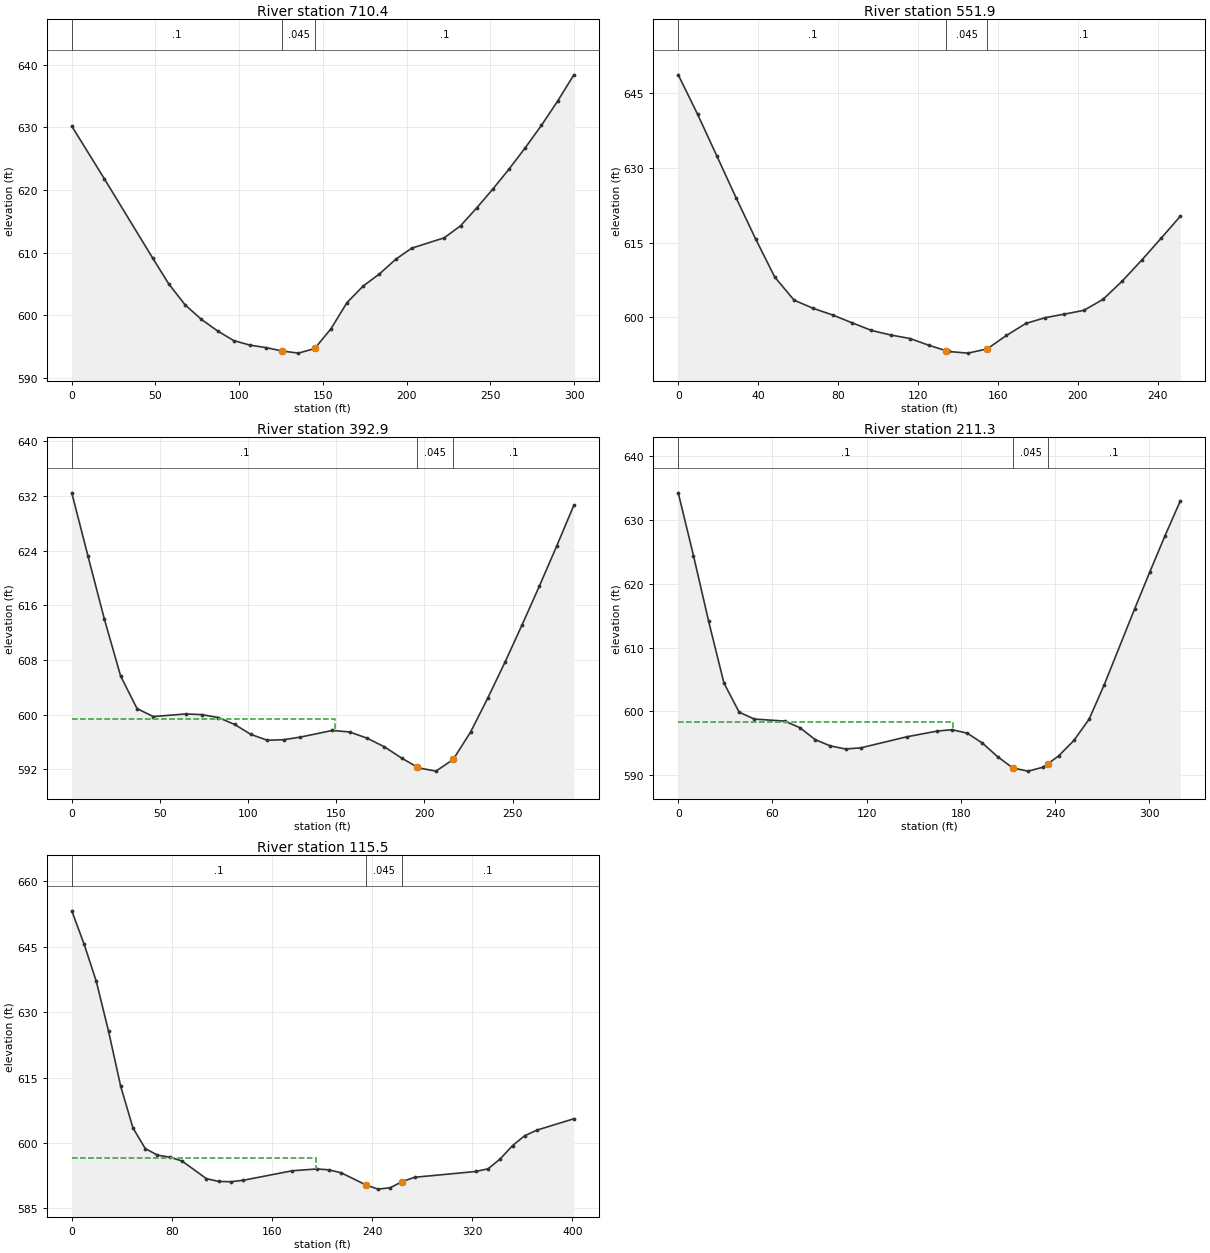
Type RM Length L Ch R = 1 ,710.4   ,158.4,158.5,158.3
XS GIS Cut Line= 2
     1802366.047       460668.47     1802066.514      460654.353
#Sta/Elev= 28
       0  630.21    19.4  621.82    48.4   609.1      58  604.98    67.7  601.66
    77.4  599.35    87.1  597.49    96.7  595.96   106.4  595.23   116.1  594.83
   125.8  594.28   135.4  593.95   145.1  594.69   154.8  597.83   164.4  602.02
   174.1  604.68   183.8   606.6   193.5  608.94   203.1  610.72   222.5  612.37
   232.2  614.28   241.8  617.12   251.5  620.15   261.2  623.35   270.8  626.72
   280.5  630.32   290.2  634.19   299.9   638.4
#Mann= 3 , 0 , 0
       0      .1       0   125.8    .045       0   145.1      .1       0
Bank Sta=125.8,145.1
XS Rating Curve= 0 ,0
Exp/Cntr=0.3,0.1

Type RM Length L Ch R = 1 ,551.9   ,160.4,159.1,157.2
XS GIS Cut Line= 2
     1802389.985      460511.338     1802138.942      460499.676
#Sta/Elev= 29
       0  648.61     9.7  640.69    19.3  632.37      29  623.93    38.7  615.75
    48.3  608.08      58  603.44    67.7  601.79    77.3  600.47      87  598.91
    96.7  597.38   106.3  596.47     116  595.76   125.7  594.37   134.2   593.3
   135.3  593.16     145  592.83   154.2  593.64   154.6  593.67   164.3  596.38
     174  598.78   183.6  599.93   193.3  600.65     203   601.4   212.6   603.6
   222.3   607.3     232  611.48   241.6  615.81   251.3  620.27
#Mann= 3 , 0 , 0
       0      .1       0   134.2    .045       0   154.6      .1       0
Bank Sta=134.2,154.6
XS Rating Curve= 0 ,0
Exp/Cntr=0.3,0.1

Type RM Length L Ch R = 1 ,392.9   ,167.3,181.6,195.5
XS GIS Cut Line= 3
     1802402.261      460383.055     1802256.791      460356.661
     1802119.915      460358.503
#Sta/Elev= 30
       0  632.46     9.2  623.19    18.5  613.96    27.7  605.64      37  600.87
    46.2   599.7    64.7  600.08    73.9  599.98    83.2  599.55    92.4  598.54
   101.6  597.08   110.9  596.23   120.1  596.31   129.4  596.68   147.8  597.67
   157.6  597.44   167.4  596.54   177.2  595.28     187  593.63     196  592.28
   196.7  592.18   206.5  591.71   216.3  593.42   226.1  597.42   235.8  602.36
   245.6  607.63   255.4  613.16   265.2  618.84     275  624.68   284.7  630.64
#Mann= 3 , 0 , 0
       0      .1       0     196    .045       0   216.3      .1       0
#XS Ineff= 2 , 0
          149.05  599.31
Permanent Ineff=
       F       F
Bank Sta=196,216.3
XS Rating Curve= 0 ,0
Exp/Cntr=0.3,0.1

Type RM Length L Ch R = 1 ,211.3   ,94.5,95.8,97.1
XS GIS Cut Line= 2
     1802436.634      460300.192     1802163.494      460133.853
#Sta/Elev= 30
       0  634.24     9.7  624.41    19.4  614.08    29.1  604.44    38.8  599.87
    48.4  598.79    67.8  598.47    77.5  597.44    87.2  595.57    96.9  594.58
   106.6   594.1   116.3  594.28   145.4     596   164.8   596.9   174.4  597.12
   184.1  596.58   193.8  595.01   203.5  592.88   213.2  591.11   222.9  590.63
   232.6  591.26   235.5  591.79   242.3  593.02     252  595.43   261.7  598.77
   271.4   604.2   290.7  616.05   300.4  621.86   310.1  627.54   319.8  632.98
#Mann= 3 , 0 , 0
       0      .1       0   213.2    .045       0   235.5      .1       0
#XS Ineff= 2 , 0
          174.78  598.35
Permanent Ineff=
       F       F
Bank Sta=213.2,235.5
XS Rating Curve= 0 ,0
Exp/Cntr=0.3,0.1

Type RM Length L Ch R = 1 ,115.5   ,100.5,115.5,130.4
XS GIS Cut Line= 2
     1802499.159      460241.763     1802167.965      460015.393
#Sta/Elev= 30
       0  653.26     9.8  645.66    19.6  637.07    29.4  625.61    39.1  612.99
    48.9  603.44    58.7   598.7    68.5  597.19    78.3  596.72    88.1  595.85
   107.6  591.79   117.4  591.16   127.2  591.09     137  591.42   176.1   593.6
   195.7  594.02   205.5  593.82   215.3  593.13   234.8  590.39   244.6  589.39
   254.4   589.7   264.2  591.14     274  592.11   322.9  593.44   332.7  594.06
   342.5  596.36   352.2  599.38     362  601.66   371.8  602.94   401.2  605.54
#Mann= 3 , 0 , 0
       0      .1       0   234.8    .045       0   264.2      .1       0
#XS Ineff= 2 , 0
          194.83  596.43
Permanent Ineff=
       F       F
Bank Sta=234.8,264.2
XS Rating Curve= 0 ,0
Exp/Cntr=0.3,0.1

Chan Stop Cuts=-1
Use User Specified Reach Order=0
Composite Channel Slope=5